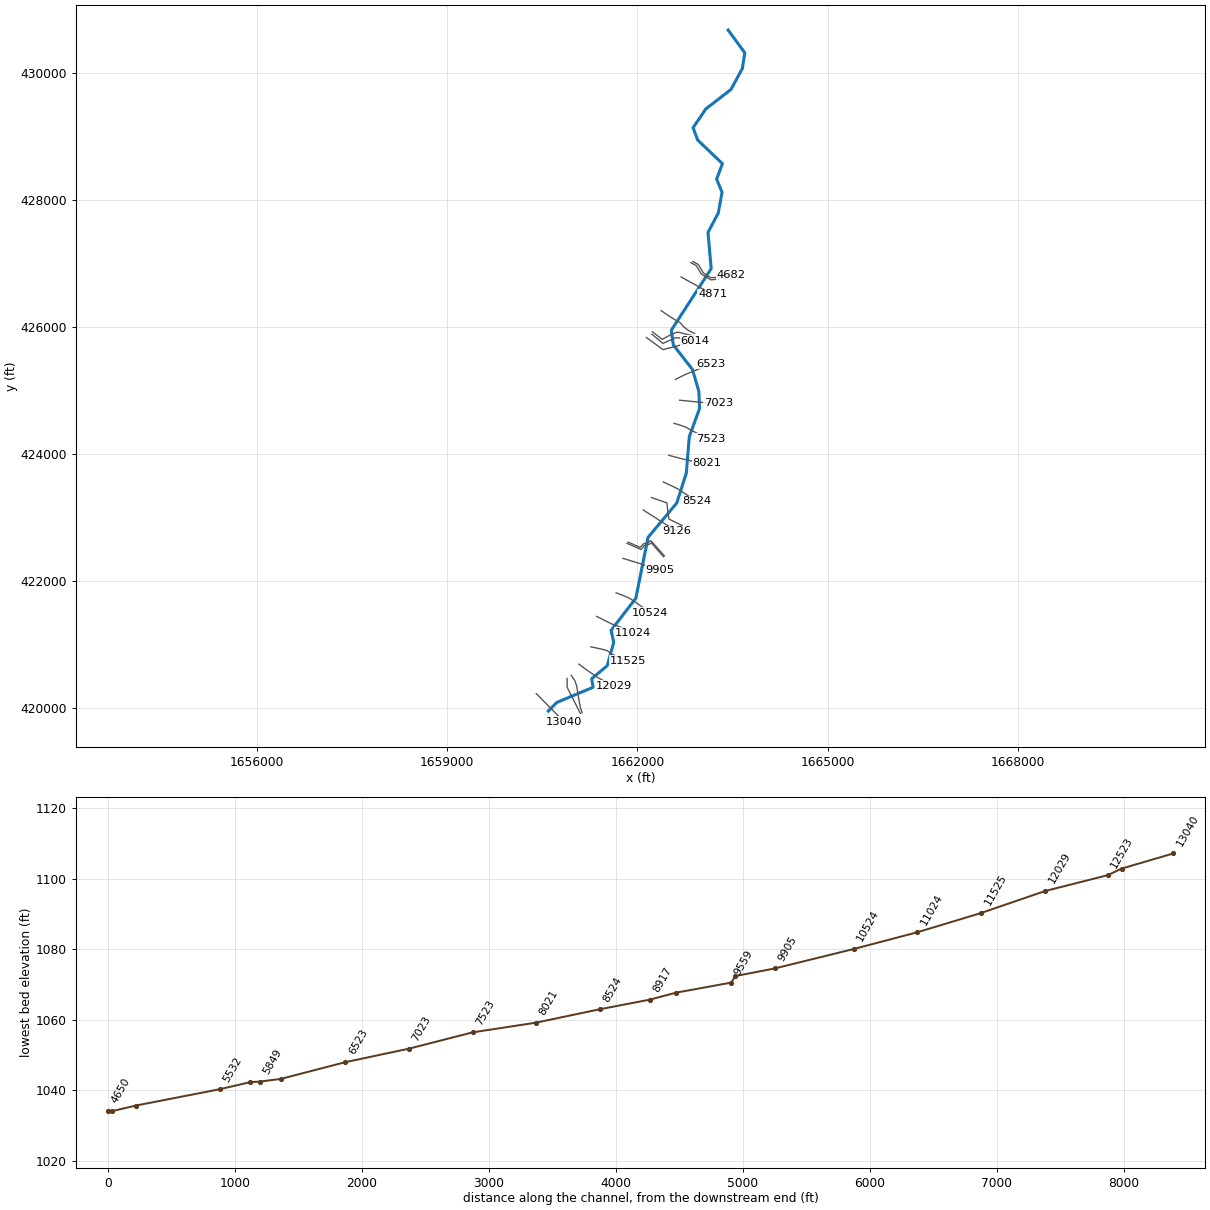
--- MILLERFK.prj (project) ---

Proj Title=MILLERFK
Current Plan=p01
Default Exp/Contr=0,0
English Units
Geom File=g01
Flow File=f01
Plan File=p01
BEGIN DESCRIPTION:
---------- MODELED AS PART OF WVEMD CTP PROGRAM, 2023----------
Stream Name: Miller Fork
Flood Zone:  AFH
Wetzel County, WV
HEC-RAS Version: RAS 6.3
Vertical Datum: NAVD88
Projection: NAD 1983 StatePlane West Virginia S FIPS 4702 (US Feet)
Terrain: 1-meter West Virginia FEMA R3 South Central (collected 2018-2020)
Land Use: 2019 NLCD
Hydrologic Method:
WV SIR2010-5033 regression equations
Additional Model Notes:
None
END DESCRIPTION:
DSS Export Rating Curves= 0
DSS Export Rating Curve Sorted= 0
DSS Export Volume Flow Curves= 0
DXF OffsetX= 0
DXF OffsetY= 0
DXF ScaleX= 0
DXF ScaleY= 0

--- MILLERFK.p01 (plan) ---

Plan Title=Floodplain
Program Version=6.30
Short Identifier=Floodplain
Geom File=g01
Flow File=f01
Subcritical Flow
K Sum by GR= 0
Std Step Tol= 0.01
Critical Tol= 0.01
Num of Std Step Trials= 20
Max Error Tol= 0.3
Flow Tol Ratio= 0.001
Split Flow NTrial= 30
Split Flow Tol= 0.02
Split Flow Ratio= 0.02
Log Output Level= 0
Friction Slope Method= 1
Unsteady Friction Slope Method= 2
Unsteady Bridges Friction Slope Method= 1
Parabolic Critical Depth
Global Vel Dist= 0 , 0 , 0
Global Log Level= 0
CheckData=True
Encroach Param=-1 ,0,0, 0
Mapping Interval=1HOUR
Computation Time Step Use Courant=        0
Computation Time Step Use Time Series=    0
Computation Time Step Count To Double=0
Computation Time Step Max Doubling=0
Computation Time Step Max Halving=0
Computation Time Step Residence Courant=0
Run HTab= 0
Run UNet= 0
Run Sediment= 0
Run PostProcess= 0
Run WQNet= 0
Run RASMapper= 0
UNET Theta= 0
UNET Theta Warmup= 0
UNET ZTol= 0
UNET ZSATol= 0
UNET MxIter= 0
UNET Max Iter WO Improvement= 0
UNET MaxInSteps= 0
UNET DtIC= 0
UNET DtMin= 0
UNET MaxCRTS= 0
UNET WFStab= 0
UNET SFStab= 0
UNET WFX= 1
UNET SFX= 1
UNET Gravity=32.17405
UNET 1D Methodology=Finite Difference
UNET DSS MLevel= 1
UNET Pardiso=0
UNET DZMax Abort= 0
UNET Use Existing IB Tables= 0
UNET Froude Reduction=False
UNET Froude Limit= 0
UNET Froude Power= 0
UNET D1 Cores= 0
UNET WindReference=Eulerian
UNET WindDragFormulation=Hsu (1988)
UNET D2 Coriolis=0
UNET D2 Cores= 0
UNET D2 Theta= 1
UNET D2 Theta Warmup= 1
UNET D2 Z Tol= 0.01
UNET D2 Volume Tol= 0.01
UNET D2 Max Iterations= 20
UNET D2 Equation= 0
UNET D2 RampUpFraction=0.1
UNET D2 TimeSlices= 1
UNET D2 Turbulence Formulation=Non-Conservative (original)
UNET D2 Eddy Viscosity=0.3
UNET D2 Transverse Eddy Viscosity=0.1
UNET D2 Smagorinsky Mixing=0
UNET D2 BCVolumeCheck=0
UNET D2 Cores=0
UNET D2 SolverType=PARDISO (Direct)
UNET D2 Minimum Iterations= 3
UNET D2 Maximum Iterations= 30
UNET D2 Restart Number= 10
UNET D2 Relaxation Coeff=1.3
UNET D2 SOR Precondition Iterations= 10
UNET D2 ILUT Maximum Fill= 8
UNET D2 ILUT Tolerance=1E-08
UNET D2 Convergence Tolerance=0.00001
UNET D1D2 MaxIter= 0
UNET D1D2 ZTol=0.01
UNET D1D2 QTol=0.1
UNET D1D2 MinQTol=1
Write IC File= 0
Write IC File at Fixed DateTime=0
Write IC File at Sim End=0
Echo Input=False
Echo Parameters=False
Echo Output=False
Write Detailed= 0
HDF Write Warmup=0
HDF Write Time Slices=0
HDF Flush=0
HDF Compression= 1
HDF Chunk Size= 1
HDF Spatial Parts= 1
HDF Use Max Rows=0
HDF Fixed Rows= 1
Calibration Method= 0
Calibration Iterations= 20
Calibration Max Change=0.05
Calibration Tolerance=0.2
Calibration Maximum=1.5
Calibration Minimum=0.5
Calibration Optimization Method= 1
WQ AD Non Conservative
WQ ULTIMATE=-1
WQ Max Comp Step=1HOUR
WQ Output Interval=15MIN
WQ Output Selected Increments= 0
WQ Output face flow=0
WQ Output face velocity=0
WQ Output face area=0
WQ Output face dispersion=0
WQ Output cell volume=0
WQ Output cell surface area=0
WQ Output cell continuity=0
WQ Output cumulative cell continuity=0
WQ Output face conc=0
WQ Output face dconc_dx=0
WQ Output face courant=0
WQ Output face peclet=0
WQ Output face adv mass=0
WQ Output face disp mass=0
WQ Output cell mass=0
WQ Output cell source sink temp=0
WQ Output nsm pathways=0
WQ Output nsm derived pathways=0
WQ Create Restart=0
WQ Fixed Restart=0
WQ System Summary=0
WQ Write To DSS=0
Sorting and Armoring Iterations= 10
XS Update Threshold= 0.02
Bed Roughness Predictor= 0
Hydraulics Update Threshold= 0.02
Energy Slope Method= 1
Volume Change Method= 1
Sediment Retention Method= 0
Sediment TS Multiplier= 1
Warm Up Method= 0
XS Weighting Method= 0
Number of US Weighted Cross Sections= 1
Number of DS Weighted Cross Sections= 1
Upstream XS Weight=0
Main XS Weight=1
Downstream XS Weight=0
Number of DS XS's Weighted with US Boundary= 1
Upstream Boundary Weight= 1
Weight of XSs Associated with US Boundary= 0
Number of US XS's Weighted with DS Boundary= 1
Downstream Boundary Weight= 0.5
Weight of XSs Associated with DS Boundary= 0.5
Percentile Method= 0
Sediment Output Level= 3
Mass or Volume Output= 0
Output Increment Type= 1
Profile and TS Output Increment= 1
Transport Output Increment 1
XS Output Flag= 0
XS Output Increment= 10
Read HDF5 Sediment Hotstart= 0
Sediment Hotstart Type= 0
Write Gradation File= 0
Read Gradation Hotstart= 0
Write HDF5 File= 1
Write Binary Output= 1
Write DSS Sediment File= 0
DSS Sediment Output Type= 1
SV Curve= 0
Specific Gage Flag= 0
Subcell Erosion Methods= 0
Subcell Deposition Methods= 0
Advection Scheme= 1
Matrix Solver= 0
Implicit Weighting Factor= 1
Maximum Outer Loop Convergence Iterations= 5
Convergence Maximum Absolute= 0.001
Convergence RMSE= 0.0001
Grain Fractions Max Abs Error= 0.001
Max Subgrid Regions= 1
Max Subgrid Length Scale= 3.402823E+38
Initial Layer Thickness= 3.402823E+38
Min Layer Thickness= 3.402823E+38
Max Layer Thickness= 3.402823E+38
Number of Layers= 5

--- MILLERFK.f01 (steady flow) ---

Flow Title=Flow
Program Version=6.30
Number of Profiles= 1
Profile Names=F01pct
River Rch & RM=MILLERFK,Main            ,13040
     851
River Rch & RM=MILLERFK,Main            ,9592
     972
River Rch & RM=MILLERFK,Main            ,6014
    1350
River Rch & RM=MILLERFK,Main            ,0
    2080
Boundary for River Rch & Prof#=MILLERFK,Main            , 1
Up Type= 0
Dn Type= 1
Dn Known WS=1002.6
DSS Import GetInterval= 0
DSS Import GetPeak= 0
DSS Import FillOption= 0

--- MILLERFK.g01 (geometry) ---

Geom Title=Geometry
Program Version=6.31

River Reach=MILLERFK        ,Main
Reach XY= 30
1660595.36741651 419950.89431884     1660726.583420085.258000016
     1661301.403420325.8499999941661278.93099999420459.585000008
     1661524.149420665.5859999951661627.03900002421034.185000017
1661585.83900002421223.8830000011661974.92800002421728.420000017
1662166.82800001422686.600999996      1662619.81423229.474000022
1662770.51100001423699.862000018      1662817.66424274.022000015
1662978.05400002424715.987000003      1662968.36 424987.86500001
1662866.57100001 425334.211000011662565.39100002425719.775000006
1662534.54600002      425953.316     1663162.023      426921.191
1663112.01000002427492.046000019     1663273.947427797.633000016
1663333.43400002428125.0310000181663247.94900002428331.693000004
1663339.60300002428575.590000018     1662949.412428949.256000012
     1662876.706429142.0380000171663080.06299999429440.795000017
     1663473.338429743.7370000031663652.90100001430075.541999996
1663691.89800002430322.083000019  1663429.378598 430681.01519537

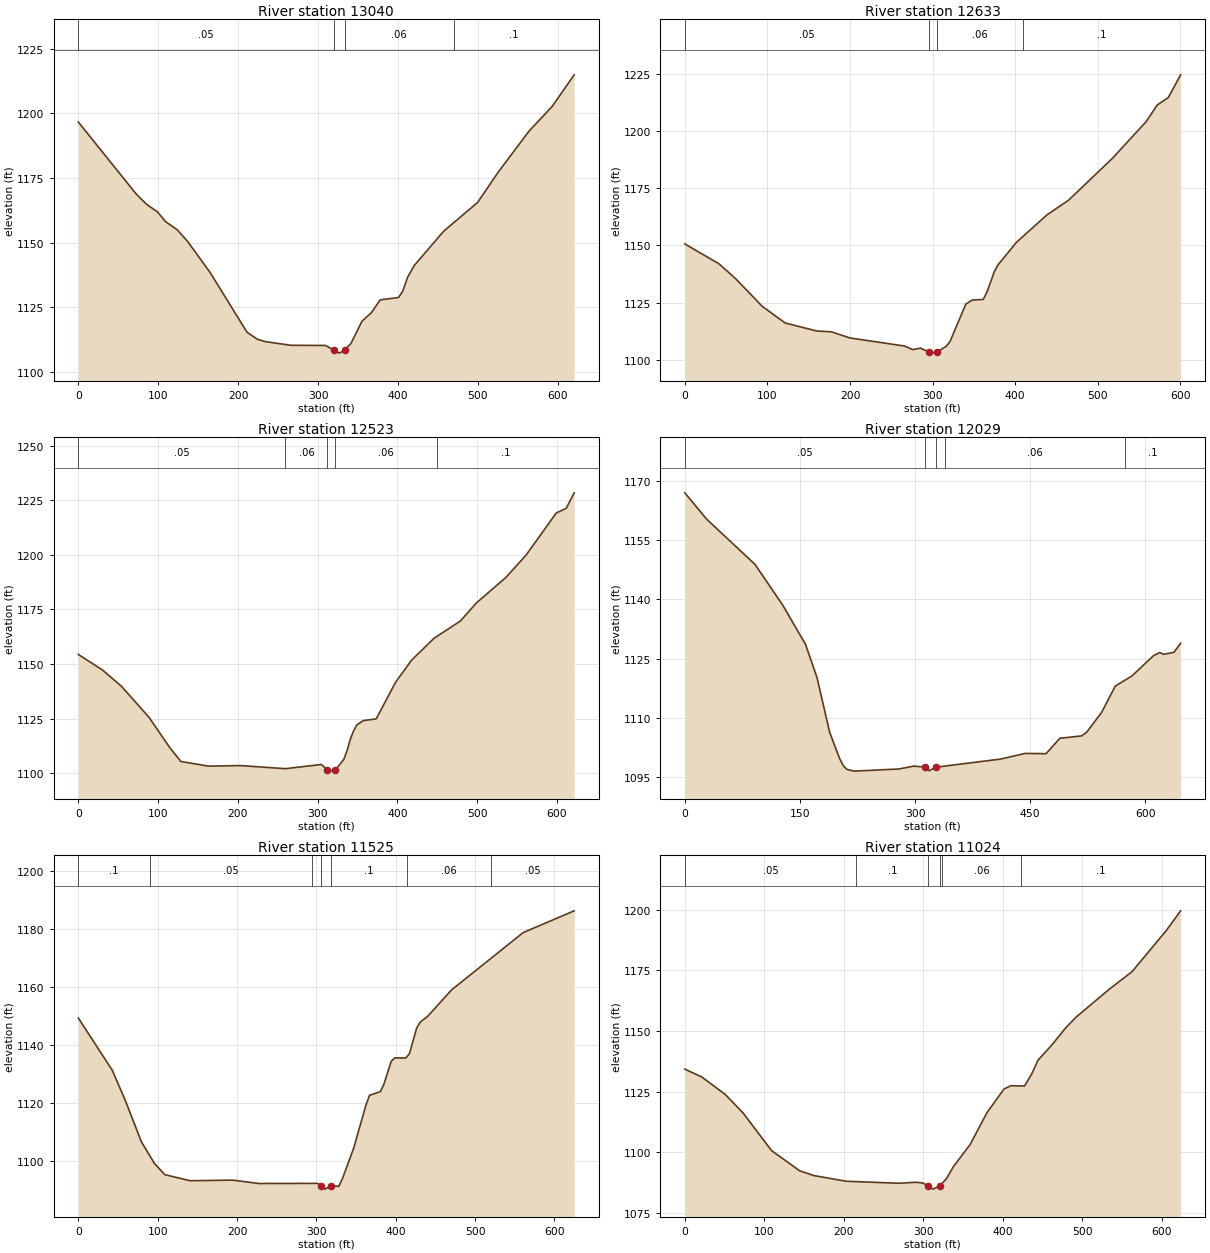
Type RM Length L Ch R = 1 ,13040   ,408.3,407.4,403.4
XS GIS Cut Line= 2
1660406.50893929420225.6559620161660842.81308965419784.293212812
#Sta/Elev= 30
       0 1196.68    72.6 1168.76    85.9  1164.7      99 1161.92   109.4 1158.07
   123.6 1155.03   136.6 1150.53   164.7 1138.55   211.2 1115.27   224.2 1112.58
   233.9 1111.67   265.9 1110.25   309.5 1110.17  319.69 1108.41   326.6 1107.21
   333.4 1108.41   341.3 1110.98     355 1119.56   366.8 1122.87   377.8 1127.83
   400.9 1128.76   406.3 1131.36   412.2 1136.65   420.5 1141.15   457.3 1154.42
   499.7 1165.54   525.7 1177.33     564 1193.12   593.1 1202.73   620.6 1214.96
#Mann= 4 ,-1,0
       0     .05       0  319.69    .045       0   333.4     .06       0
     470      .1       0
Bank Sta=319.69,333.4
XS Rating Curve= 0 ,0
Exp/Cntr(USF)=0,0
Exp/Cntr=0.3,0.1

Type RM Length L Ch R = 1 ,12633   ,110.2,109.7,106.9
XS GIS Cut Line= 3
   1660892.36265420465.988228299   1660892.36265 420326.45994259
 1661100.1707351419915.296802787
#Sta/Elev= 30
       0 1150.65    41.5 1141.92    61.5 1135.47    93.7 1123.37   121.5 1116.08
   159.6 1112.58   177.5 1112.22   199.9 1109.55   265.8 1106.02   276.1 1104.44
   285.1 1105.09   295.6 1103.42   298.5 1102.91  305.65 1103.43   316.5 1105.91
     321 1107.94   340.2 1124.32   347.8  1126.1   361.3 1126.37   365.8 1129.62
   374.7 1138.52   378.9 1141.37   401.6 1151.38   438.5 1163.35   464.4 1169.69
   518.2 1188.23   558.5 1204.08   571.9 1211.34   585.4 1214.65   600.2 1224.52
#Mann= 4 ,-1,0
       0     .05       0   295.6    .045       0  305.65     .06       0
  409.53      .1       0
Bank Sta=295.6,305.65
XS Rating Curve= 0 ,0
Exp/Cntr(USF)=0,0
Exp/Cntr=0.3,0.1

Type RM Length L Ch R = 1 ,12523   ,488.9,493.5,496.8
XS GIS Cut Line= 6
1660958.70386909420514.0257397591661013.59286693420430.177482262
1661043.16564243420345.9358528411661083.31221567420099.183721676
   1661100.65995420013.2862556731661128.79473625419923.021344334
#Sta/Elev= 30
       0 1154.42    30.5 1147.25    54.1 1139.84    88.8 1125.59   114.7 1111.77
   128.6 1105.46   163.1 1103.32   203.2 1103.58   259.7 1102.16   304.7 1104.08
   312.4 1101.59   316.8 1101.04  322.34 1101.57     333 1106.48   337.1 1110.61
   341.1 1115.71   345.1 1119.42   349.2 1122.16   357.3 1124.16   373.5 1124.94
   397.7 1141.65   417.9 1151.82   446.3 1161.89     479  1169.7   499.4 1178.07
   536.3 1189.71   561.5 1199.91   599.2  1219.1   611.8  1221.3   621.7 1228.35
#Mann= 5 ,-1,0
       0     .05       0   259.5     .06       0   312.4    .045       0
  322.34     .06       0  449.55      .1       0
Bank Sta=312.4,322.34
XS Rating Curve= 0 ,0
Exp/Cntr(USF)=0,0
Exp/Cntr=0.3,0.1

Type RM Length L Ch R = 1 ,12029   ,497.1,504.8,502
XS GIS Cut Line= 6
 1661077.5717416420690.0306370851661228.97826293420578.417671338
  1661382.623953 420475.139006511661448.82198334 420438.64925009
1661533.48487176420397.1398186681661623.73239468420347.566098928
#Sta/Elev= 30
       0 1166.98    28.6 1160.29    91.5 1148.87   127.7 1138.53   157.3 1128.64
   172.2 1120.27   188.8 1106.37   201.6 1099.79   206.4 1097.97   211.3 1096.98
   220.5 1096.54     279 1097.08   298.3 1097.81  313.22 1097.56   318.5 1096.64
   327.1 1097.53   411.1 1099.58   443.5 1101.02   470.8 1100.96   488.7 1104.85
   517.2 1105.46   523.8 1106.41   543.1 1111.39     561 1118.08   582.6 1120.61
   610.8 1125.77   619.1 1126.56   623.7  1126.1   637.4 1126.61   646.1 1128.91
#Mann= 5 ,-1,0
       0     .05       0  313.22    .045       0   327.1     .05       0
  338.99     .06       0  573.12      .1       0
Bank Sta=313.22,327.1
XS Rating Curve= 0 ,0
Exp/Cntr(USF)=0,0
Exp/Cntr=0.3,0.1

Type RM Length L Ch R = 1 ,11525   ,494.6,500.8,498.7
XS GIS Cut Line= 6
1661266.14223059420963.2003663331661448.76916192420924.274591178
 1661523.4799705420902.9603293391661605.92435943 420846.27704376
1661672.25296693420809.5609098371661844.74901301420744.075804591
#Sta/Elev= 30
       0 1149.37    42.8 1131.32    59.1 1120.98    79.5 1106.63    95.9 1099.19
     109 1095.29     141  1093.2   194.4 1093.41   227.7 1092.24   301.2 1092.29
   305.81091.531   311.1  1090.3   318.1 1091.53   328.3 1091.25   333.2 1094.16
   347.2 1104.59   362.3 1119.14     367 1122.68   380.7 1123.96     385 1126.42
   394.4 1134.46     399 1135.61   412.7 1135.56   417.3 1137.03   426.4 1145.88
     431 1147.99   440.3 1149.95   470.4 1159.07   560.6 1178.84   624.9 1186.36
#Mann= 7 ,-1,0
       0      .1       0      90     .05       0  294.43      .1       0
   305.8    .045       0   318.1      .1       0  414.48     .06       0
   520.3     .05       0
Bank Sta=305.8,318.1
XS Rating Curve= 0 ,0
Exp/Cntr(USF)=0,0
Exp/Cntr=0.3,0.1

Type RM Length L Ch R = 1 ,11024   ,500.9,499.9,496.9
XS GIS Cut Line= 6
1661358.91008967421442.2391064171661593.90076143421323.781010002
1661688.33823659421290.6088322551661758.75968367421263.879883096
1661839.77002034421229.1995062531661927.43782401421188.074260429
#Sta/Elev= 30
       0  1134.3    21.3 1131.07    50.8  1123.9    73.3 1116.23   109.2 1100.69
   144.5  1092.4   162.2 1090.44   203.2 1088.09   269.8 1087.27   290.9 1087.69
   299.4 1087.38  305.941086.127   312.1 1084.85   320.6 1086.17   329.1 1089.18
   337.6 1094.04   358.8 1103.23   380.1 1116.42   401.5 1126.13   410.1 1127.46
   427.2 1127.35   435.8 1132.06   444.4  1138.1   461.8 1144.33   479.2 1151.39
   492.3 1155.81   533.5 1167.16   562.4 1174.45   605.7 1191.49   623.5 1199.53
#Mann= 6 ,-1,0
       0     .05       0  215.89      .1       0  305.94    .045       0
   320.6      .1       0  323.17     .06       0  423.26      .1       0
Bank Sta=305.94,320.6
XS Rating Curve= 0 ,0
Exp/Cntr(USF)=0,0
Exp/Cntr=0.3,0.1

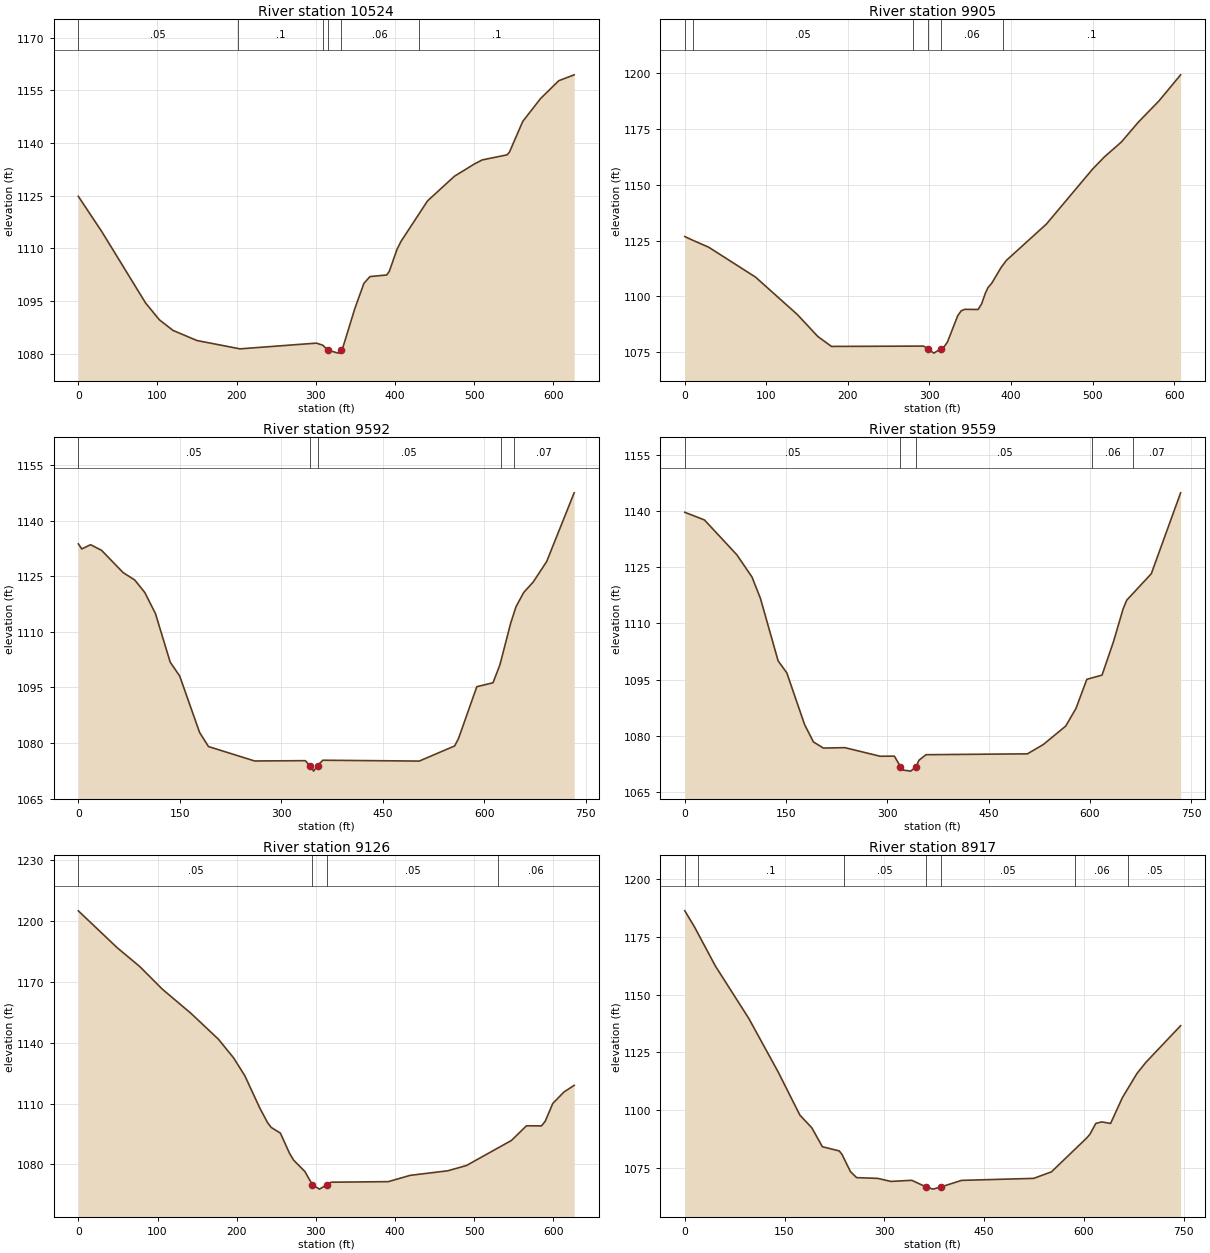
Type RM Length L Ch R = 1 ,10524   ,615.7,619.4,619.9
XS GIS Cut Line= 6
1661664.19852109421813.8702529221661756.61533101421779.545190334
1661842.24344058421744.5029375851661910.37355368421705.523356751
1661993.67817709 421648.985740171662202.97729917421501.277046084
#Sta/Elev= 30
       0 1124.79    29.8 1114.68      85  1094.4   102.4 1089.61   119.7 1086.58
   149.9 1083.71   204.2 1081.34   300.7 1082.97     309 1082.37   314.8 1081.02
   328.3 1080.12     332 1080.99   334.5 1081.95   349.3 1092.81   360.8    1100
   368.4 1101.92   389.6 1102.39   392.8 1103.39   402.6 1109.68   407.5  1111.9
   441.2  1123.5   475.1  1130.5   500.5 1134.02   510.3 1135.16   541.7 1136.61
   544.6 1137.36   561.5 1146.14   583.8  1152.6   606.9 1157.72   626.4  1159.4
#Mann= 6 ,-1,0
       0     .05       0  201.11      .1       0   309.6     .06       0
   314.8    .045       0     332     .06       0  430.28      .1       0
Bank Sta=314.8,332
XS Rating Curve= 0 ,0
Exp/Cntr(USF)=0,0
Exp/Cntr=0.3,0.1

Type RM Length L Ch R = 1 ,9905    ,307.8,312.8,312.9
BEGIN DESCRIPTION:
Structure 3 XS 4
END DESCRIPTION:
XS GIS Cut Line= 2
1661772.19261386422357.0524779391662353.53878498422178.930757351
#Sta/Elev= 30
       0  1126.8      10  1125.1    29.2 1122.05    86.8 1108.63     138  1091.9
   163.1 1082.08   179.8 1077.62   292.8 1077.77  298.571076.493   305.3 1074.62
   313.7 1076.47   317.9 1077.43   322.1 1079.59   334.6 1091.32   338.8 1093.51
     343 1094.22   359.7 1094.16   363.9  1096.6   368.6 1101.49   371.8 1103.96
   376.4 1105.92   387.8  1112.9   394.2 1116.08   443.4 1132.38   499.9 1156.93
   514.5 1162.44   535.4 1169.13   556.3 1178.06   581.4 1187.49     608 1199.18
#Mann= 6 ,-1,0
       0      .1       0      10     .05       0     280     .06       0
  298.57    .045       0   313.7     .06       0     390      .1       0
Bank Sta=298.57,313.7
XS Rating Curve= 0 ,0
Exp/Cntr(USF)=0,0
Exp/Cntr=0.3,0.1

Type RM Length L Ch R = 1 ,9592    ,31.3,32.3,36.4
BEGIN DESCRIPTION:
Structure 3 XS 3
END DESCRIPTION:
XS GIS Cut Line= 6
 1661835.4603963422592.902248381 1662057.6454394422497.021565878
1662109.27349921422559.7127813611662174.73050361422573.541725953
1662220.82698559422599.3557558571662410.74449131422381.780360946
#Sta/Elev= 30
       0 1133.73     5.1 1132.37    18.1 1133.51    34.3    1132    66.1 1126.01
    83.5 1123.97    98.2 1120.64     114 1114.94   135.8 1101.85   149.9 1098.07
   179.3 1082.86   192.4 1079.07   260.6 1075.18   335.6 1075.26  342.341073.896
   347.8 1072.44   353.7 1073.94   361.4 1075.38     504 1075.15   556.3 1079.23
     562 1081.21   589.1 1095.21     613 1096.27   623.2 1101.09   639.1  1112.3
     647 1116.77   658.3 1120.59   672.5 1123.46   692.4 1128.98     733  1147.5
#Mann= 5 ,-1,0
       0     .05       0  342.34    .045       0   353.7     .05       0
  624.23     .06       0  644.23     .07       0
Bank Sta=342.34,353.7
XS Rating Curve= 0 ,0
Exp/Cntr(USF)=0,0
Exp/Cntr=0.3,0.1

Type RM Length L Ch R = 1 ,9559    ,436.2,433.6,421
BEGIN DESCRIPTION:
Structure 3 XS 2
END DESCRIPTION:
XS GIS Cut Line= 6
1661853.47674531422612.8574154271662041.55039176422530.805677516
1662099.63195904422588.8872448011662166.01089308422601.794259754
1662211.18544542422635.9056564141662425.07312177422397.125879795
#Sta/Elev= 30
       0  1139.6    29.1 1137.56    77.1 1128.26    99.5 1122.35     112 1116.66
   138.2 1099.99   151.1 1096.78   177.4    1083   190.5 1078.37   205.2 1076.73
     237 1076.84   289.3 1074.55   310.4 1074.57  319.421071.789   322.5 1070.88
   334.6 1070.58   342.7 1071.79   346.7 1073.47   357.3 1074.96   507.4 1075.19
     531 1077.68   564.1 1082.59   579.3 1087.29   595.4 1095.06   617.9 1096.18
   634.9 1105.12   649.1 1113.83   654.5 1116.17   690.9 1123.23   734.3 1144.79
#Mann= 5 ,-1,0
       0     .05       0  319.42    .045       0   342.7     .05       0
  603.71     .06       0  663.71     .07       0
Bank Sta=319.42,342.7
XS Rating Curve= 0 ,0
Exp/Cntr(USF)=0,0
Exp/Cntr=0.3,0.1

Type RM Length L Ch R = 1 ,9126    ,217.6,209,200.1
BEGIN DESCRIPTION:
Structure 3 XS 1
END DESCRIPTION:
XS GIS Cut Line= 2
1662090.75728384423119.5346645271662618.90155466422783.250546098
#Sta/Elev= 30
       0 1205.13      49 1186.94    77.5 1177.66   105.9 1166.52   142.2 1154.53
   176.9 1141.75     196 1132.57   210.3 1123.69   229.1 1107.82   238.7 1100.76
   243.5 1098.22   255.2 1095.37   266.8 1085.34   271.9 1082.04   286.1 1076.44
   295.6 1069.84   304.5 1067.74  313.621069.852   319.3 1071.16   391.4 1071.43
   418.9 1074.53   466.3 1076.78     490 1079.38   546.9 1091.77   565.9 1099.01
   584.9 1098.96   589.6 1101.29   599.1 1110.04   613.3 1115.72   626.1 1118.97
#Mann= 4 ,-1,0
       0     .05       0   295.6    .045       0  313.62     .05       0
     530     .06       0
Bank Sta=295.6,313.62
XS Rating Curve= 0 ,0
Exp/Cntr(USF)=0,0
Exp/Cntr=0.3,0.1

Type RM Length L Ch R = 1 ,8917    ,382.3,392.5,400.5
BEGIN DESCRIPTION:
Low water crossing
END DESCRIPTION:
XS GIS Cut Line= 6
 1662220.2402974423314.9436193581662464.95001651423231.856133333
1662472.91730969423149.906832048 1662484.2991571423063.404791803
1662496.81918924422975.7645668181662702.83062719422875.604309692
#Sta/Elev= 30
       0 1186.35    14.4 1179.48    45.9 1162.48    96.4 1139.64   140.6 1116.42
   173.1 1097.81     191 1092.33   206.9 1084.12   232.2 1082.31   236.4 1080.81
   249.1 1073.34   258.4 1070.73     290 1070.41     310 1069.09   341.3 1069.57
   362.7 1066.73   373.4 1065.75   385.1 1066.69   416.1 1069.54   524.7 1070.41
   551.4 1073.25   604.7 1088.01   609.2 1089.52   618.1 1094.23     627 1094.88
   640.3 1094.21   658.1 1105.44     680 1115.89   693.7  1120.8   745.6 1136.58
#Mann= 7 ,-1,0
       0     .05       0      20      .1       0     240     .05       0
   362.7    .045       0   385.1     .05       0  586.54     .06       0
  666.54     .05       0
Bank Sta=362.7,385.1
XS Rating Curve= 0 ,0
Exp/Cntr(USF)=0,0
Exp/Cntr=0.3,0.1

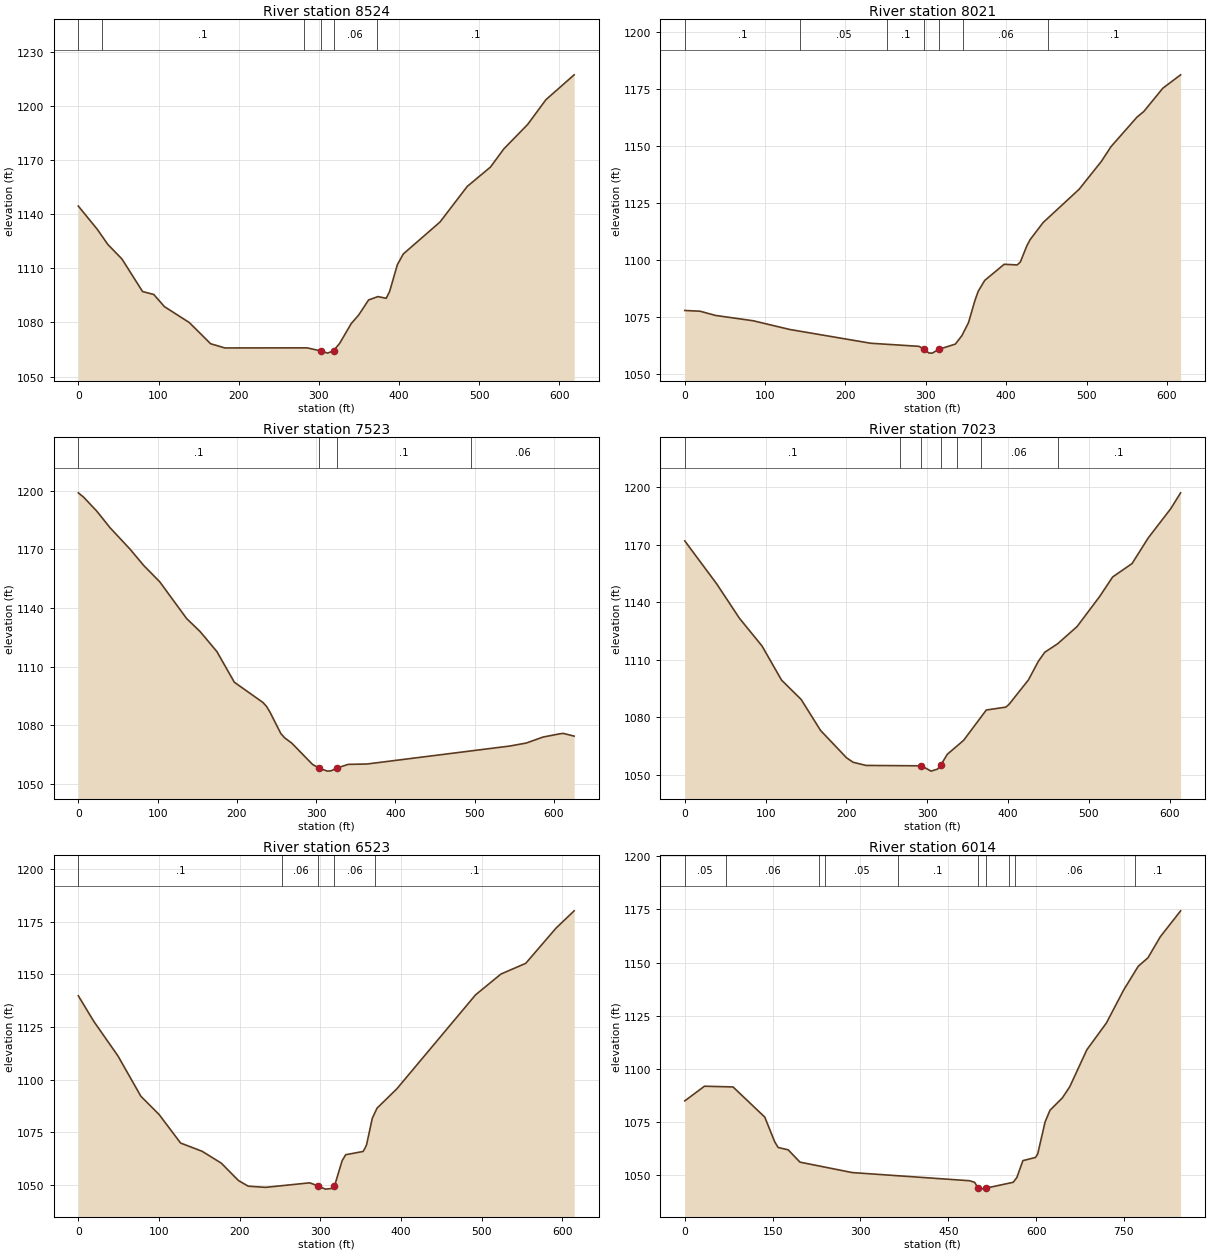
Type RM Length L Ch R = 1 ,8524    ,498.9,503.2,504.7
XS GIS Cut Line= 6
1662406.67702301423561.3815216721662573.54643993 423482.98043175
1662641.70509626423447.5559619221662726.45623909423392.877593592
1662860.83359501423301.5047448431662942.85869342423255.812907085
#Sta/Elev= 30
       0 1144.48    23.6 1131.64    36.8 1123.22    54.4 1115.18    80.1 1097.15
    94.1 1095.52   107.4 1088.77   138.4 1079.98     165 1068.23   182.8  1065.9
   285.4 1065.95   302.7 1064.22     311 1063.03   318.4 1064.46   325.9 1068.42
   340.3 1079.36   349.7 1084.16     362 1092.48   373.7 1094.35     384  1093.4
   388.2 1097.13   397.9 1112.02   405.3 1117.96   451.1 1135.66     485 1155.34
     514 1166.08   530.6 1176.11   560.4 1189.69   583.2 1203.42   618.4 1217.18
#Mann= 6 ,-1,0
       0     .05       0      30      .1       0  281.19     .06       0
   302.7    .045       0   318.4     .06       0  372.05      .1       0
Bank Sta=302.7,318.4
XS Rating Curve= 0 ,0
Exp/Cntr(USF)=0,0
Exp/Cntr=0.3,0.1

Type RM Length L Ch R = 1 ,8021    ,496.7,497.9,486.8
XS GIS Cut Line= 6
1662493.75526093423980.847218171  1662741.566117423915.626548082
1662839.49111801423894.0658956771662914.80166292423883.683698595
1663003.32248326423873.6591123341663098.17399959423862.779540926
#Sta/Elev= 30
       0 1077.91      19 1077.59    38.2 1075.74    85.2  1073.4   130.7 1069.58
   231.4 1063.55   291.6 1062.19   297.6 1060.94   303.9 1059.26     308 1059.22
   316.2  1060.9   336.7 1063.17   344.9  1066.9   353.1  1072.6   361.2 1082.41
   365.2 1086.35   373.3  1091.1   397.5 1098.16   413.7 1097.87   417.7 1099.21
   425.7 1106.25   429.8 1108.96   445.9 1116.42   490.8 1131.04   518.4 1143.22
   530.5 1149.73   562.7 1162.61   571.3 1165.12   594.9  1175.3   617.1 1181.18
#Mann= 7 ,-1,0
       0      .1       0  143.75     .05       0  251.25      .1       0
   297.6    .045       0   316.2      .1       0  346.25     .06       0
  452.54      .1       0
Bank Sta=297.6,316.2
XS Rating Curve= 0 ,0
Exp/Cntr(USF)=0,0
Exp/Cntr=0.3,0.1

Type RM Length L Ch R = 1 ,7523    ,494.1,499.6,501.3
XS GIS Cut Line= 6
1662577.58645809424484.2776417581662669.64368868424457.789177671
1662752.75867993424428.343698502  1662974.431793424309.768476337
1663060.06318343424276.3604066671663153.22310209424245.198395506
#Sta/Elev= 30
       0 1198.96     6.8  1196.7    23.4 1189.53    40.1 1181.05    65.1 1170.18
    82.6 1161.72   102.7 1153.42   136.6  1134.6   153.6 1127.95   174.8 1117.69
   196.8    1102   232.9 1091.63   237.4 1089.63   241.9 1086.59   255.5 1075.69
   260.4 1073.49   269.3 1070.81   295.4 1059.93     304 1057.95   314.3 1056.48
   318.8 1056.62   325.8 1057.99   340.3 1059.94     364 1060.12   544.2 1069.32
   565.1 1070.86   586.4 1073.94   607.5 1075.59   611.7  1075.8   625.5  1074.4
#Mann= 4 ,-1,0
       0      .1       0     304    .045       0   325.8      .1       0
  495.38     .06       0
Bank Sta=304,325.8
XS Rating Curve= 0 ,0
Exp/Cntr(USF)=0,0
Exp/Cntr=0.3,0.1

Type RM Length L Ch R = 1 ,7023    ,494.3,500.9,505.2
XS GIS Cut Line= 6
1662664.94520725424848.9399701651662919.84528801424823.834705427
  1663019.305719 424813.245487751663094.12741975424806.520763665
1663181.97074801424804.5247046651663276.22908968424804.605741262
#Sta/Elev= 30
       0 1172.07    39.4 1149.69    67.5 1131.76    95.6 1117.18   119.7  1099.4
   143.9 1089.33     168  1073.1   200.1 1058.83   208.2  1056.5   224.2 1054.85
   292.6 1054.64   304.7 1051.87   312.7 1052.93  316.39 1054.83   324.8 1060.69
   344.9 1067.93     373 1083.79   397.1 1085.28   401.1 1086.72   425.2 1099.55
   437.3 1109.15   445.3 1113.93   461.3 1118.39   485.3 1127.36   513.2 1143.03
   529.3 1153.25   553.3 1160.25   573.3 1173.62   601.3 1188.98   613.4 1197.19
#Mann= 7 ,-1,0
       0      .1       0  266.13     .06       0   292.6    .045       0
  316.39     .06       0  336.13      .1       0  366.16     .06       0
  461.28      .1       0
Bank Sta=292.6,316.39
XS Rating Curve= 0 ,0
Exp/Cntr(USF)=0,0
Exp/Cntr=0.3,0.1

Type RM Length L Ch R = 1 ,6523    ,506,508.3,506.2
XS GIS Cut Line= 6
 1662599.2140395425175.3431887631662683.76964468425218.993363917
1662762.37086542425258.059886843 1662832.1174451425285.635619089
1662924.71995017425323.3976826671663160.84579025425423.902074844
#Sta/Elev= 30
       0 1139.82      19 1127.78    49.1 1111.28    77.5 1092.15     100 1083.52
   126.8 1069.91   153.3 1066.03   177.1 1060.41   198.5 1052.12   210.6 1049.44
   232.1 1048.88   286.8 1051.03   297.4 1049.55   306.2 1048.04   314.1 1048.35
   316.61049.696   318.5 1050.77     327 1061.55   331.4 1064.37     353 1065.92
   355.3 1067.46   357.3 1069.14   364.4 1081.71   370.3 1086.49   394.9  1095.7
   492.4 1140.27   523.8 1150.13   554.6 1155.23   592.1 1171.93   614.6 1180.15
#Mann= 5 ,-1,0
       0      .1       0  252.93     .06       0   297.4    .045       0
   316.6     .06       0  367.94      .1       0
Bank Sta=297.4,316.6
XS Rating Curve= 0 ,0
Exp/Cntr(USF)=0,0
Exp/Cntr=0.3,0.1

Type RM Length L Ch R = 1 ,6014    ,156.2,165.6,165.3
BEGIN DESCRIPTION:
Structure 2 XS 4
END DESCRIPTION:
XS GIS Cut Line= 6
1662141.71367591425837.0652111811662402.59798499425645.468938437
1662641.04203984 425707.139041171662721.37652484425733.504473999
1662811.45639718425760.2015990911662905.24787626425789.598850012
#Sta/Elev= 30
       0 1084.85    33.6 1091.75    82.4 1091.41   136.6  1077.2   153.7 1065.49
   159.5 1062.89   176.6 1061.79   196.7    1056   285.9 1051.09   486.4 1047.24
   494.9 1046.52  500.911043.819   502.9 1043.29   514.6 1043.77   560.8 1046.51
   567.1 1048.73   577.4 1056.71   598.9  1058.2   602.7 1059.84   615.3  1074.9
   623.7 1080.43   644.8 1086.25   657.4 1091.47   686.6 1108.89     720 1121.51
   749.6 1137.09   774.3  1148.2   791.1 1152.26     812  1162.1   846.8 1174.34
#Mann= 10 ,-1,0
       0     .05       0      70     .06       0     230      .1       0
     240     .05       0  363.68      .1       0  500.91    .045       0
   514.6      .1       0  553.68     .05       0  563.68     .06       0
  768.47      .1       0
Bank Sta=500.91,514.6
XS Rating Curve= 0 ,0
Exp/Cntr(USF)=0,0
Exp/Cntr=0.3,0.1

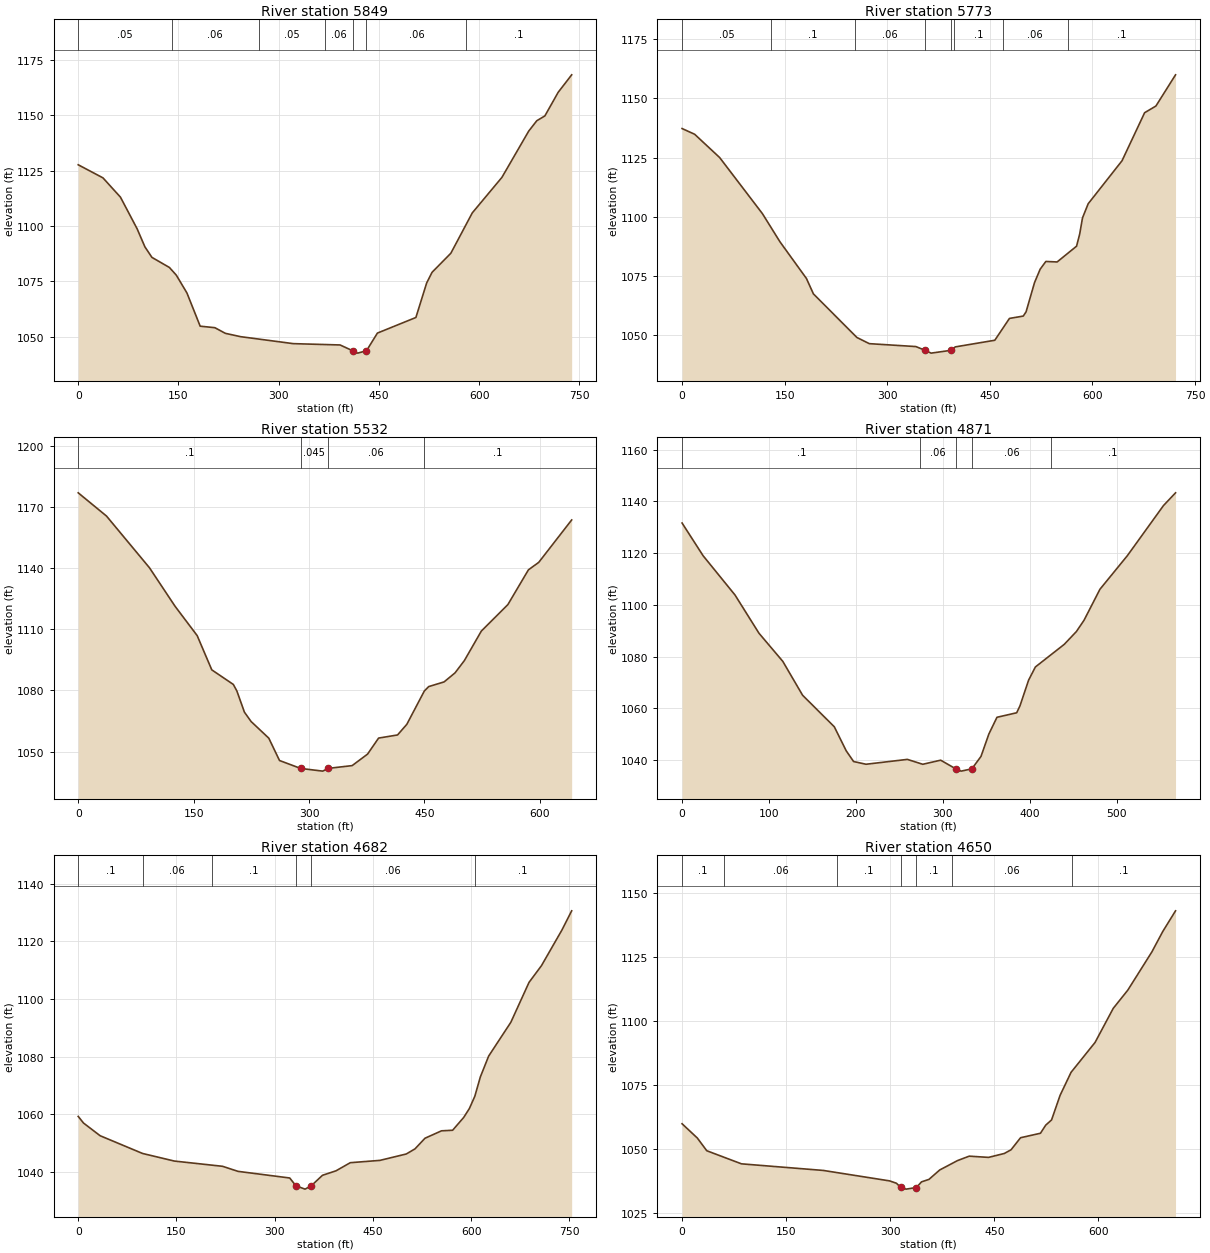
Type RM Length L Ch R = 1 ,5849    ,75.3,75.4,76.2
BEGIN DESCRIPTION:
Structure 2 XS 3
END DESCRIPTION:
XS GIS Cut Line= 5
1662227.82454581425889.4448113131662400.69996719425743.534995936
 1662431.5480673 425756.919814061662605.79276916425834.915061558
1662892.05192221425806.704014591
#Sta/Elev= 30
       0  1127.7      37 1121.79    63.2 1113.06    88.2 1098.72    99.8 1090.58
   110.3 1085.82   136.5 1081.25   146.9 1077.74   162.7 1069.72   182.5 1054.71
   204.5 1054.02   220.2 1051.47     243 1049.96   321.8 1046.81   391.9 1046.21
411.35521043.506   418.2 1042.52431.3552 1043.58   447.7 1051.58   505.3 1058.64
   521.4 1074.24   529.5 1079.08   557.6 1087.69   589.7 1105.95     634 1121.99
   674.1 1142.92   686.2 1147.62   698.3  1149.8   718.2 1160.47   738.4 1168.38
#Mann= 7 ,-1,0
       0     .05       0     140     .06       0  269.85     .05       0
  369.85     .06       0411.3552    .045       0431.3552     .06       0
  580.75      .1       0
Bank Sta=411.3552,431.3552
XS Rating Curve= 0 ,0
Exp/Cntr(USF)=0,0
Exp/Cntr=0.3,0.1

Type RM Length L Ch R = 1 ,5773    ,260.6,240.9,225.4
BEGIN DESCRIPTION:
Structure 2 XS 2
END DESCRIPTION:
XS GIS Cut Line= 6
1662237.72612559425927.2590210991662388.63848405425807.503465878
1662525.67256604425880.9108503751662618.23881929425919.829566166
1662663.37856878425916.3304836321662883.99127933 425860.60661311
#Sta/Elev= 30
       0 1137.24    18.4 1134.82    54.9    1125   117.5 1101.28   143.1  1089.4
   181.8 1073.91     192  1067.4   255.6 1048.98   273.7 1046.37   341.8 1045.14
355.21931043.566   364.1 1042.37392.62941043.535   399.4    1045   457.2 1047.81
   478.6 1057.03   498.8 1058.02   502.9 1059.81   515.3  1072.2   523.5 1077.82
   531.8 1081.09   548.3 1080.88   576.7 1087.54   581.3  1092.7   585.4  1099.5
   593.7 1105.47   643.2 1123.64   676.2 1143.92   692.7 1146.75   721.4 1159.93
#Mann= 8 ,-1,0
       0     .05       0     130      .1       0  252.65     .06       0
355.2193    .045       0392.6294     .06       0  398.11      .1       0
  468.62     .06       0   563.9      .1       0
Bank Sta=355.2193,392.6294
XS Rating Curve= 0 ,0
Exp/Cntr(USF)=0,0
Exp/Cntr=0.3,0.1

Type RM Length L Ch R = 1 ,5532    ,656.9,660.9,659.3
BEGIN DESCRIPTION:
Structure 2 XS 1
END DESCRIPTION:
XS GIS Cut Line= 6
1662372.79749759426260.5171995011662523.69319317426157.723441839
1662676.87792617426066.7022984181662728.28497559426006.638442174
1662803.90096609425947.5873791721662898.55760093425900.968706012
#Sta/Elev= 30
       0 1177.11    36.8 1165.68    92.6 1140.29   125.9 1121.35   154.6 1106.96
   173.6 1090.12   201.6 1082.95   206.2 1079.74     216 1069.34   224.7 1064.73
   247.7 1056.55   261.6 1045.58   289.1 1041.68   317.8 1040.36   324.81041.706
     356 1043.07     376 1048.71   390.4  1056.6     415 1058.13   427.1 1063.38
   449.8 1079.72   455.5  1081.9   475.5  1084.2   489.7 1088.63   501.8 1094.65
   523.9 1109.18   558.4  1122.2   585.1 1139.27   598.5 1142.94   641.3 1163.78
#Mann= 4 ,-1,0
       0      .1       0   289.1    .045       0   324.8     .06       0
  449.89      .1       0
Bank Sta=289.1,324.8
XS Rating Curve= 0 ,0
Exp/Cntr(USF)=0,0
Exp/Cntr=0.3,0.1

Type RM Length L Ch R = 1 ,4871    ,188.4,189.1,188
BEGIN DESCRIPTION:
Structure 1 XS 4
END DESCRIPTION:
XS GIS Cut Line= 3
1662687.08016805426792.0316813111662751.68898411426755.239626683
1663184.43523514426517.863276648
#Sta/Elev= 30
       0 1131.67    24.2 1119.03      61  1103.8    88.5 1089.05   115.9 1078.18
   138.7 1065.07   175.2 1052.87   188.9 1043.58   197.4 1039.43   211.7 1038.38
   259.3 1040.26     277 1038.37   297.6 1039.95   315.3 1036.55   321.2 1035.72
  333.511036.611     344  1041.4   353.1 1050.09   362.4 1056.54   385.1 1058.29
   388.9    1061   398.8  1070.9   406.6    1076   439.8 1084.74   453.8  1089.7
   462.6 1094.07   480.9 1106.05   512.5 1119.06     554 1138.41   567.9 1143.35
#Mann= 5 ,-1,0
       0      .1       0  274.35     .06       0   315.3    .045       0
  333.51     .06       0  424.35      .1       0
Bank Sta=315.3,333.51
XS Rating Curve= 0 ,0
Exp/Cntr(USF)=0,0
Exp/Cntr=0.3,0.1

Type RM Length L Ch R = 1 ,4682    ,31.9,32,31.9
BEGIN DESCRIPTION:
Structure 1 XS 3
END DESCRIPTION:
XS GIS Cut Line= 6
1662840.71461289427016.3919775251662927.32978094426969.851580896
1663005.73989678426837.674528488 1663157.3327874426745.075915501
1663261.79932406426756.0245241841663467.81628894426827.682250735
#Sta/Elev= 30
       0 1059.33     8.1 1057.03    33.5 1052.63    98.3 1046.48   146.8 1043.85
   220.5 1042.03     244 1040.28     323 1037.98332.5258 1035.26   346.5 1034.12
     356  1035.3     373 1038.91   393.7 1040.47   415.5 1043.28   460.9 1044.09
     501  1046.3   514.3 1048.07   529.6 1051.76   554.8 1054.33   571.8 1054.53
   588.7 1058.97   597.4 1062.07   605.7 1066.32   614.1 1072.99   626.8 1080.23
   660.7 1091.96   688.5  1105.8   707.5  1111.6   738.8 1123.98   753.6  1130.6
#Mann= 6 ,-1,0
       0      .1       0   98.33     .06       0  203.91      .1       0
332.5258    .045       0     356     .06       0  605.44      .1       0
Bank Sta=332.5258,356
XS Rating Curve= 0 ,0
Exp/Cntr(USF)=0,0
Exp/Cntr=0.3,0.1

Type RM Length L Ch R = 1 ,4650    ,319.1,326.2,329.4
BEGIN DESCRIPTION:
Structure 1 XS 2
END DESCRIPTION:
XS GIS Cut Line= 6
1662872.74513779427034.0614532791662959.36030584426987.521056651
1663037.77042168426855.344004243 1663152.7719249426779.920940439
1663253.58493097426783.6547554791663461.01513742426855.059645593
#Sta/Elev= 30
       0 1059.76      22 1054.18    35.6 1049.22    85.6  1044.1   203.6 1041.52
   299.1 1037.44   308.9 1036.53   315.3  1034.9     323 1034.22  337.761034.848
   345.1 1037.05   355.9 1038.03   371.3 1041.69   397.1 1045.38   413.9  1047.1
   441.7 1046.62   464.5 1048.15   474.2 1049.59   487.9  1054.3   516.6 1056.05
   524.2 1059.22   532.6 1061.25   544.9 1070.87   560.7 1079.85   595.3 1091.53
   621.5 1104.84   642.5 1111.96   677.1 1126.86   692.8 1134.83   711.3 1142.95
#Mann= 7 ,-1,0
       0      .1       0      60     .06       0  223.91      .1       0
   315.3    .045       0  337.76      .1       0  388.81     .06       0
   561.9      .1       0
Bank Sta=315.3,337.76
XS Rating Curve= 0 ,0
Exp/Cntr(USF)=0,0
Exp/Cntr=0.3,0.1