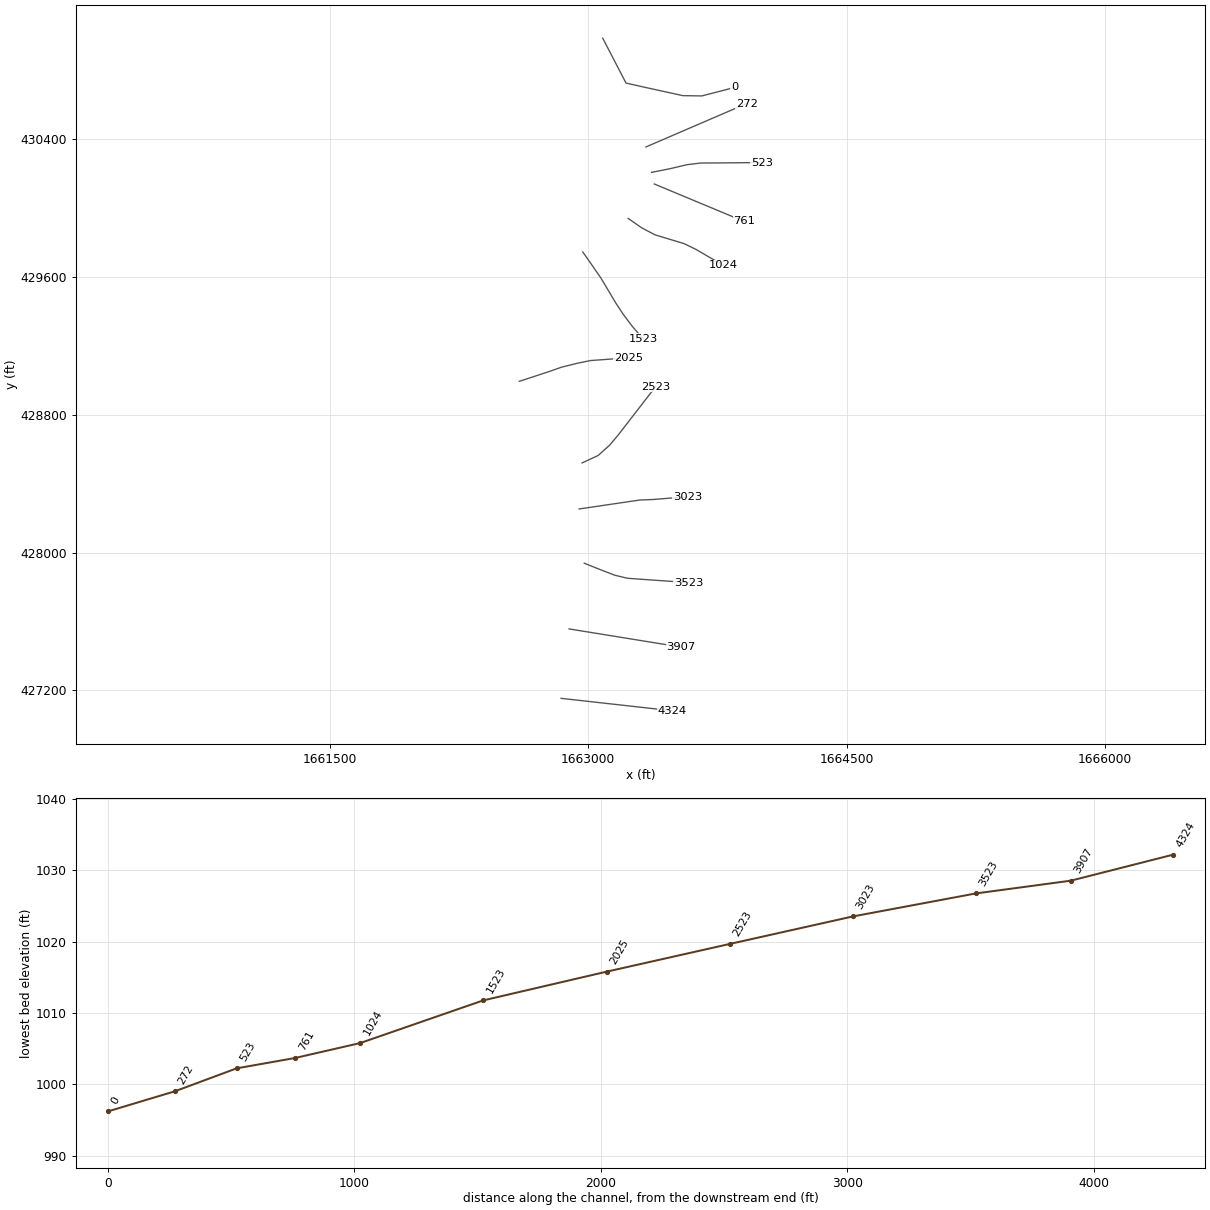
HEC-RAS study MILLERFK.prj: MILLERFK

--- MILLERFK.g01 (geometry) --- (continued)

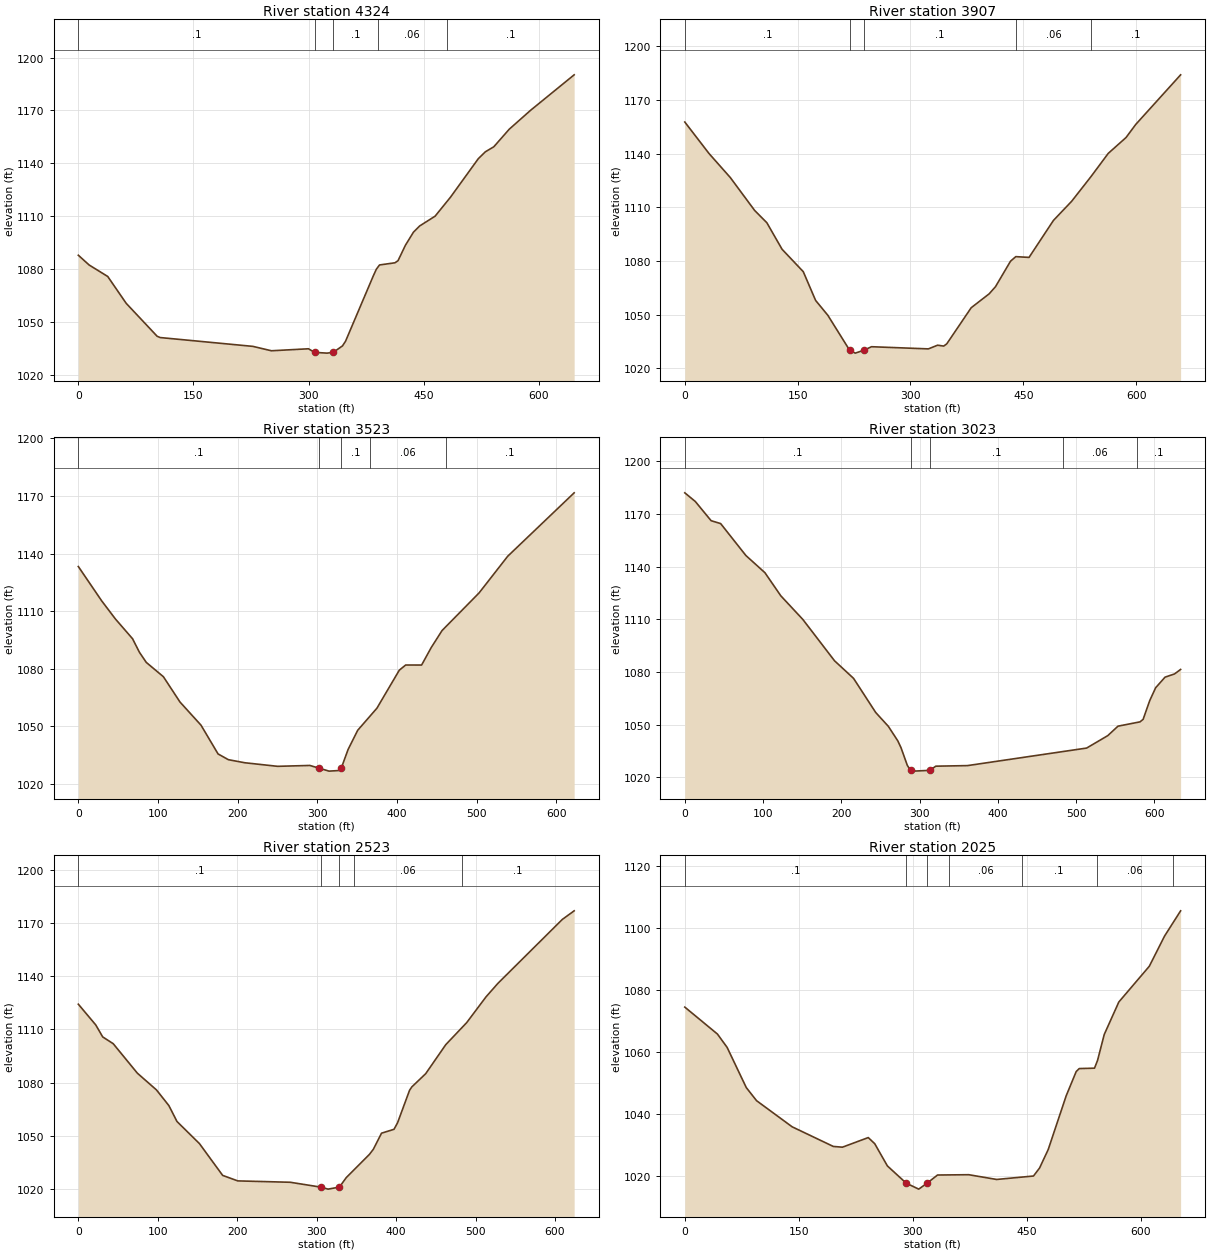
Type RM Length L Ch R = 1 ,4324    ,416.2,417.2,417.2
BEGIN DESCRIPTION:
Structure 1 XS 1
END DESCRIPTION:
XS GIS Cut Line= 2
1662842.06508776 427154.257804371663484.22610777427082.594320736
#Sta/Elev= 30
       0 1087.79    14.1 1082.24    38.3 1075.73    62.4 1060.46   102.7 1041.77
   106.7 1041.03   227.5 1036.02   251.6 1033.53   299.9 1034.66   307.9 1032.62
     324 1032.19   332.1 1032.62   344.2 1036.29   348.2 1038.94   384.4 1076.09
   388.4  1079.9   392.5 1082.26   412.6  1083.5   416.6  1084.7   426.2 1093.44
   436.7 1100.89   444.8 1104.42   464.9 1109.97     485 1120.78   521.2 1142.62
   530.4 1146.54   541.4 1149.38   561.5 1159.35   589.3 1170.09   646.1 1190.25
#Mann= 5 ,-1,0
       0      .1       0   307.9    .045       0   332.1      .1       0
     390     .06       0     480      .1       0
Bank Sta=307.9,332.1
XS Rating Curve= 0 ,0
Exp/Cntr(USF)=0,0
Exp/Cntr=0.3,0.1

Type RM Length L Ch R = 1 ,3907    ,380.6,383.9,386.7
XS GIS Cut Line= 2
1662888.43557717427557.5405456031663539.02759526427452.153069671
#Sta/Elev= 30
       0 1157.72    32.1 1140.17    60.5 1126.68    92.9 1108.27   109.1 1101.41
   129.3 1086.59   157.5 1074.06   173.9 1057.99   190.1 1049.71  219.271030.051
   226.6 1028.53   237.7 1030.09   248.2 1032.11   323.8  1030.9     336 1032.96
   344.1 1032.47   348.2  1033.7   380.7  1053.9   404.6 1061.68     413 1065.67
     433 1079.93     440 1082.47   457.6 1082.04     490 1102.69   514.3 1113.44
     540 1127.24   562.9  1140.2   586.5 1149.04   599.4 1156.35   659.1 1184.11
#Mann= 5 ,-1,0
       0      .1       0  219.27    .045       0   237.7      .1       0
     440     .06       0     540      .1       0
Bank Sta=219.27,237.7
XS Rating Curve= 0 ,0
Exp/Cntr(USF)=0,0
Exp/Cntr=0.3,0.1

Type RM Length L Ch R = 1 ,3523    ,492.3,500,500.2
XS GIS Cut Line= 6
1662976.84878293 427938.869485841663068.55988559427902.357091665
1663153.78149992427869.4063701781663227.74755934 427851.58521159
  1663489.596117427833.1052616691663583.11528692427826.526862755
#Sta/Elev= 30
       0 1133.23    29.3 1115.37    46.6  1105.9    68.1 1095.63    76.7  1088.6
    85.3 1083.33   106.8 1075.87   127.6 1062.72     154 1050.66   175.4  1035.7
   188.3 1032.71   208.9 1031.11   250.1 1029.25   290.6  1029.7   302.1 1028.31
   314.7 1026.75   326.7 1027.05   329.3 1028.31   330.7 1029.03   338.7 1038.09
   350.7 1048.01   374.8 1059.49   402.9 1079.28   410.9 1081.97   430.9 1081.96
     443 1091.06   456.6 1099.92   503.1 1119.51     539 1138.58   622.4 1171.58
#Mann= 5 ,-1,0
       0      .1       0   302.1    .045       0   329.3      .1       0
  366.16     .06       0  461.16      .1       0
Bank Sta=302.1,329.3
XS Rating Curve= 0 ,0
Exp/Cntr(USF)=0,0
Exp/Cntr=0.3,0.1

Type RM Length L Ch R = 1 ,3023    ,488.5,500,507.4
XS GIS Cut Line= 6
1662946.83014217428254.1093409211663200.32537009428291.581378832
1663299.25036909   428306.2040531663375.91852283428309.162380427
1663470.94720417428316.8933360871663575.87973709428323.410711512
#Sta/Elev= 30
       0 1182.11    13.4 1177.19    33.6 1166.24    45.8 1164.58    78.1 1146.37
   102.4 1136.59   122.6 1123.47   150.9 1109.91   191.3 1086.41   215.6 1076.39
   243.9 1056.95   260.1 1049.02   272.2 1040.74   276.3 1036.82   284.3 1026.83
   288.4 1023.93   292.4 1023.52  313.051023.962   320.7 1026.34   361.1 1026.66
   513.4 1036.66   540.4 1043.74   553.5 1049.14   581.6 1051.59   585.6 1053.04
     594 1063.68   601.6 1071.04   613.6 1077.07   625.7  1078.9   633.5 1081.47
#Mann= 5 ,-1,0
       0      .1       0   288.4    .045       0  313.05      .1       0
  482.97     .06       0  578.32      .1       0
Bank Sta=288.4,313.05
XS Rating Curve= 0 ,0
Exp/Cntr(USF)=0,0
Exp/Cntr=0.3,0.1

Type RM Length L Ch R = 1 ,2523    ,507.9,498,490
XS GIS Cut Line= 6
1662964.26252201428521.6839369981663056.99265151428564.652026922
1663123.72381726 428624.570870341663172.69812876428682.388340011
1663234.06939709428761.6841131751663390.94244292428964.304114759
#Sta/Elev= 30
       0 1124.31    21.9  1112.6    30.7  1105.8    43.9 1101.97    74.3 1085.29
    98.4 1075.79     114 1066.92   124.2 1057.93   152.5 1045.41   181.7 1027.43
   200.7 1024.32   266.8 1023.54   305.3 1020.79   314.4 1019.66   328.7  1020.8
   337.2 1026.13   366.5 1039.34   371.4 1042.22   381.7 1051.32   397.4 1053.51
   401.9 1057.22     417  1075.6   419.9 1077.53   437.3 1084.99   462.6 1101.43
   488.9 1113.88   513.2 1128.44   528.2  1136.1   609.3 1172.28   624.2 1177.15
#Mann= 5 ,-1,0
       0      .1       0   305.3    .045       0   328.7      .1       0
  347.66     .06       0  482.93      .1       0
Bank Sta=305.3,328.7
XS Rating Curve= 0 ,0
Exp/Cntr(USF)=0,0
Exp/Cntr=0.3,0.1

Type RM Length L Ch R = 1 ,2025    ,519.5,502,486.7
XS GIS Cut Line= 6
1662599.17138867428995.4516902571662772.64217034429052.244227588
1662843.73881292429077.4098596721662940.89216192429101.420966506
1663014.40579443429116.3231676671663233.16782409429132.042952508
#Sta/Elev= 30
       0 1074.51    42.9 1065.83    55.7 1061.51    80.9 1048.55    94.4 1044.33
   141.2  1035.9   195.4 1029.56   207.4 1029.32   241.4 1032.42   249.9 1030.45
   266.6 1023.27   291.3 1017.72   307.8 1015.79  319.281017.788   332.5 1020.34
   373.6 1020.44   410.3 1018.91   458.8 1020.02   466.8  1022.6   478.2 1028.57
   501.8 1045.88     515 1053.72     519 1054.68   539.1 1054.81   543.1 1057.32
   551.9 1065.68   571.1 1076.16   611.2 1087.69   631.3 1097.44   652.4 1105.57
#Mann= 7 ,-1,0
       0      .1       0   291.3    .045       0  319.28      .1       0
  347.95     .06       0  443.04      .1       0  541.96     .06       0
  641.96      .1       0
Bank Sta=291.3,319.28
XS Rating Curve= 0 ,0
Exp/Cntr(USF)=0,0
Exp/Cntr=0.3,0.1

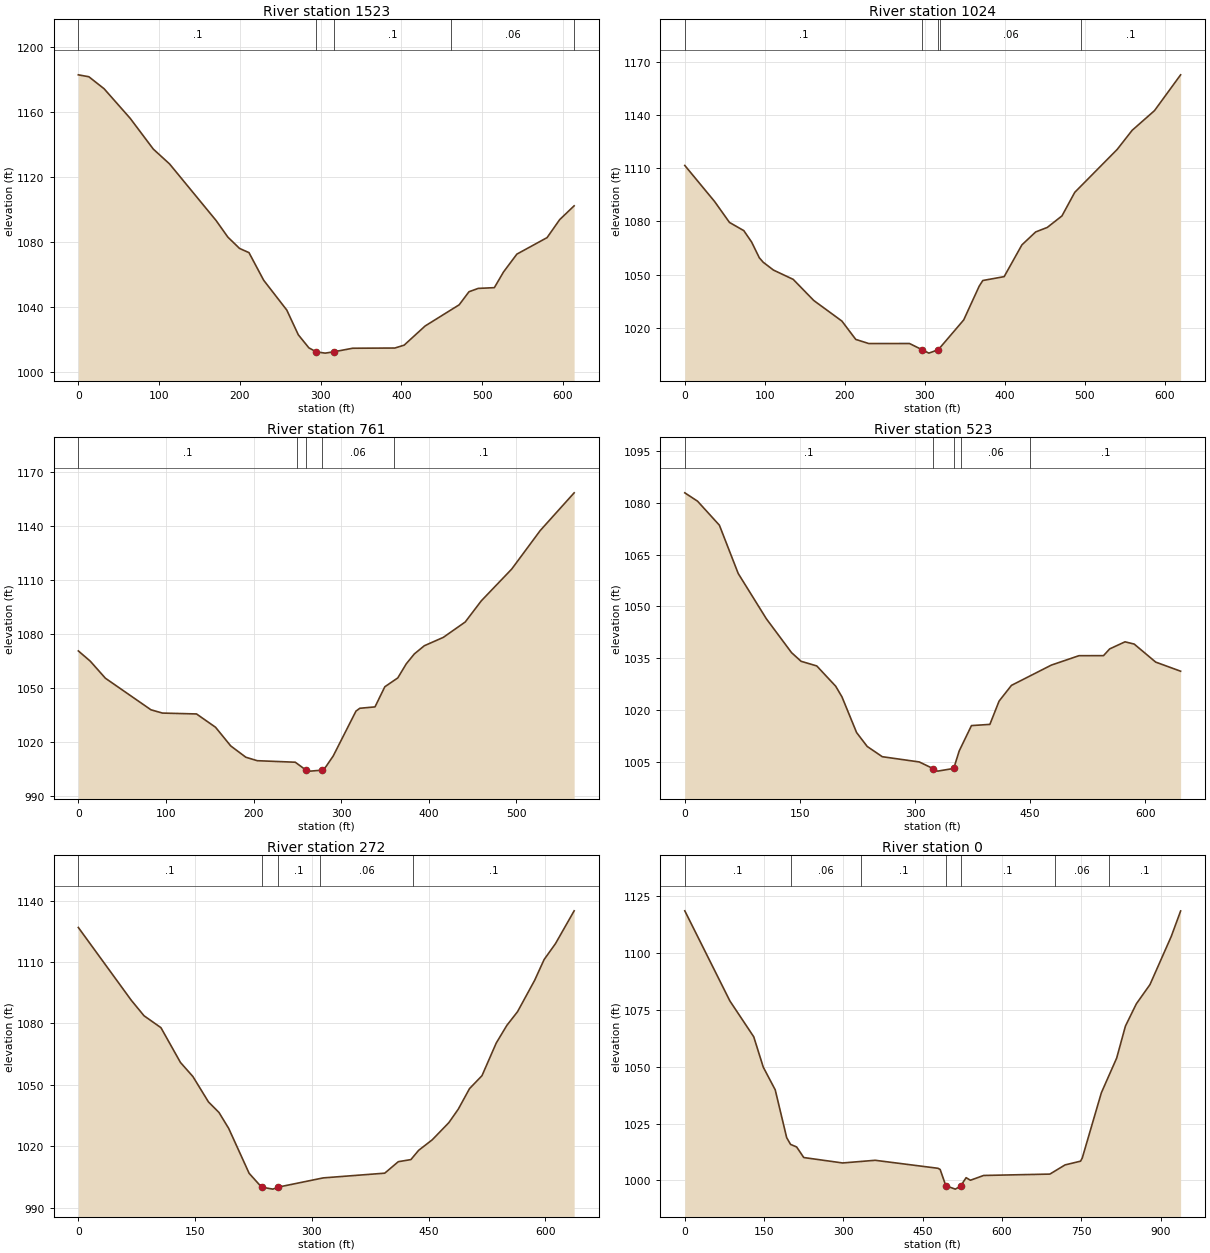
Type RM Length L Ch R = 1 ,1523    ,489.7,499.4,505.3
XS GIS Cut Line= 6
1662968.55286776429746.5141645071663072.12090209429597.380276427
1663161.76934484429447.0767712591663203.21283151429384.454849258
1663255.95222734429314.2154884191663317.95144717429243.022061259
#Sta/Elev= 30
       0 1183.15      13 1181.97    31.9 1174.58    64.2 1156.36    92.8 1137.43
     113 1128.25   170.7 1093.35   185.1 1083.23   199.6 1076.24   211.3 1073.64
   229.5 1056.64   258.1 1038.28   272.4 1023.03   285.5 1014.98   294.7 1012.52
   305.7 1011.75   316.3 1012.56   339.7 1014.76   391.9 1014.89   403.4 1016.65
   429.4 1028.46   471.6 1041.52   483.7 1049.55   495.1 1051.61   515.1 1052.07
   526.5 1061.75     543 1072.72   580.4 1082.89     596 1093.96   613.9 1102.46
#Mann= 5 ,-1,0
       0      .1       0   294.7    .045       0   316.3      .1       0
   461.7     .06       0  613.94      .1       0
Bank Sta=294.7,316.3
XS Rating Curve= 0 ,0
Exp/Cntr(USF)=0,0
Exp/Cntr=0.3,0.1

Type RM Length L Ch R = 1 ,1024    ,263.8,262.6,261.5
XS GIS Cut Line= 6
1663231.55266984429941.7978946721663310.18112151429886.979434758
 1663388.4194821429845.9677057561663556.20031451429795.448121756
1663624.96133184429761.9865745011663784.15097409429669.376851588
#Sta/Elev= 30
       0 1111.49    37.2 1091.23    55.9 1079.39    73.8 1074.78    83.6 1068.32
    93.2 1059.48      98 1056.99   110.9 1052.55   135.6 1047.31   161.3 1035.42
   196.5 1023.82   213.8  1013.5     230 1011.18     281 1011.19   296.9 1007.66
   305.2 1005.77  316.981007.674   348.8 1024.46   368.2  1043.5   372.7 1046.68
   399.4 1048.86   421.6 1066.75   438.8 1074.03   453.3 1076.57   471.7 1083.07
   487.7 1096.35   540.8 1120.54   559.4 1131.26   587.4 1142.37   620.1 1162.55
#Mann= 5 ,-1,0
       0      .1       0   296.9    .045       0  316.98      .1       0
   319.2     .06       0  495.89      .1       0
Bank Sta=296.9,316.98
XS Rating Curve= 0 ,0
Exp/Cntr(USF)=0,0
Exp/Cntr=0.3,0.1

Type RM Length L Ch R = 1 ,761     ,231.9,238.1,241.9
XS GIS Cut Line= 2
1663383.59508977430141.541685672 1663905.9355551429923.788499358
#Sta/Elev= 30
       0 1070.52    13.6 1064.83    30.9 1055.33    82.9 1037.78      96 1035.96
   134.9 1035.47   156.6 1028.08   173.9 1017.72   191.2 1011.41   204.2 1009.49
   247.6 1008.64  259.92 1004.23   264.9 1003.69   277.9 1004.23   282.3 1005.97
   290.9  1012.1   316.9 1037.06   321.3 1038.63   338.6  1039.4   349.8 1050.58
   364.6  1055.5   374.3 1063.35   383.5 1068.84   394.9 1073.39   416.6 1078.05
   441.6  1086.6   459.9 1098.34   494.6 1115.99   527.2 1137.44   565.9 1158.39
#Mann= 5 ,-1,0
       0      .1       0     250     .06       0  259.92    .045       0
   277.9     .06       0     360      .1       0
Bank Sta=259.92,277.9
XS Rating Curve= 0 ,0
Exp/Cntr(USF)=0,0
Exp/Cntr=0.3,0.1

Type RM Length L Ch R = 1 ,523     ,241.5,251.1,254.4
XS GIS Cut Line= 6
1663367.88212159430209.0529375821663474.71753784430230.379010424
 1663573.2475245430253.6450400051663652.41600133430263.396660924
1663752.41612943430263.8218569161664008.65610251430266.071196258
#Sta/Elev= 30
       0 1082.92    16.6  1080.5    45.1 1073.53    69.6 1059.54   106.3  1046.4
   139.1 1036.59   151.5 1034.08     172 1032.73   196.7 1026.84   204.9 1023.73
   223.9 1013.41   237.7 1009.39   257.4 1006.41   305.6 1004.89  323.421002.986
   329.6 1002.23   350.5 1003.01   357.6 1008.07   373.6 1015.43   397.6 1015.78
   409.6 1022.53   425.7 1027.09   477.7 1032.97   513.7  1035.7   545.7 1035.71
   553.7 1037.66   573.7 1039.72   585.7 1039.07   613.7 1033.84   646.2  1031.2
#Mann= 5 ,-1,0
       0      .1       0  323.42    .045       0   350.5      .1       0
  359.95     .06       0  449.95      .1       0
Bank Sta=323.42,350.5
XS Rating Curve= 0 ,0
Exp/Cntr(USF)=0,0
Exp/Cntr=0.3,0.1

Type RM Length L Ch R = 1 ,272     ,279.7,271.8,261.5
XS GIS Cut Line= 2
1663334.64148446430356.6177382811663919.55462238430608.611839732
#Sta/Elev= 30
       0 1126.93      68 1091.35    84.4 1083.76   106.1 1077.95   131.2 1060.93
   147.2 1054.04   167.1 1041.68   180.7 1036.46   193.2 1028.66   219.4 1006.74
   235.4  999.98   249.9  999.01  256.83999.9958   314.6  1004.5   393.6 1006.81
     411 1012.42   427.2 1013.45   437.1 1017.97   454.6 1023.12   475.9 1031.49
   488.1 1038.13   502.5 1048.15   518.5 1054.47   536.8 1070.42   550.4 1079.04
   564.2 1085.77   586.2 1101.14   598.3 1111.24   612.9 1119.03   636.9 1135.07
#Mann= 5 ,-1,0
       0      .1       0   235.4    .045       0  256.83      .1       0
     310     .06       0     430      .1       0
Bank Sta=235.4,256.83
XS Rating Curve= 0 ,0
Exp/Cntr(USF)=0,0
Exp/Cntr=0.3,0.1

Type RM Length L Ch R = 1 ,0       ,230.9,236.3,241.5
BEGIN DESCRIPTION:
Structure XS 4
END DESCRIPTION:
XS GIS Cut Line= 6
1663084.02974235430988.2860449211663219.11109367430727.906859641
1663304.43441384430708.5020428051663548.59567092430654.787255217
1663659.44366111430653.0637656841663849.21704817430702.061532839
#Sta/Elev= 30
       0 1118.38    85.3 1078.81   130.4 1063.07   148.4 1049.75     171 1039.79
   192.7 1018.78     200 1015.84   211.5  1014.7     225 1010.06   298.5 1007.68
     360 1008.85   478.8 1005.34   482.9 1004.83  493.69997.6691   511.6  996.19
   521.5   997.5     532 1001.21   540.2 1000.09   565.2 1002.19   690.4 1002.79
   719.2 1006.83   748.4 1008.46   751.7 1009.86   787.8  1038.5   816.8 1053.76
   833.3 1067.76   853.9 1077.53   879.7 1085.98     920 1107.15   937.7 1118.31
#Mann= 7 ,-1,0
       0      .1       0     200     .06       0  333.33      .1       0
  493.69    .045       0   521.5      .1       0  700.84     .06       0
   801.7      .1       0
Bank Sta=493.69,521.5
XS Rating Curve= 0 ,0
Exp/Cntr=0.3,0.1
LCMann Table=0

Chan Stop Cuts=-1
Use User Specified Reach Order=0
Composite Channel Slope=5